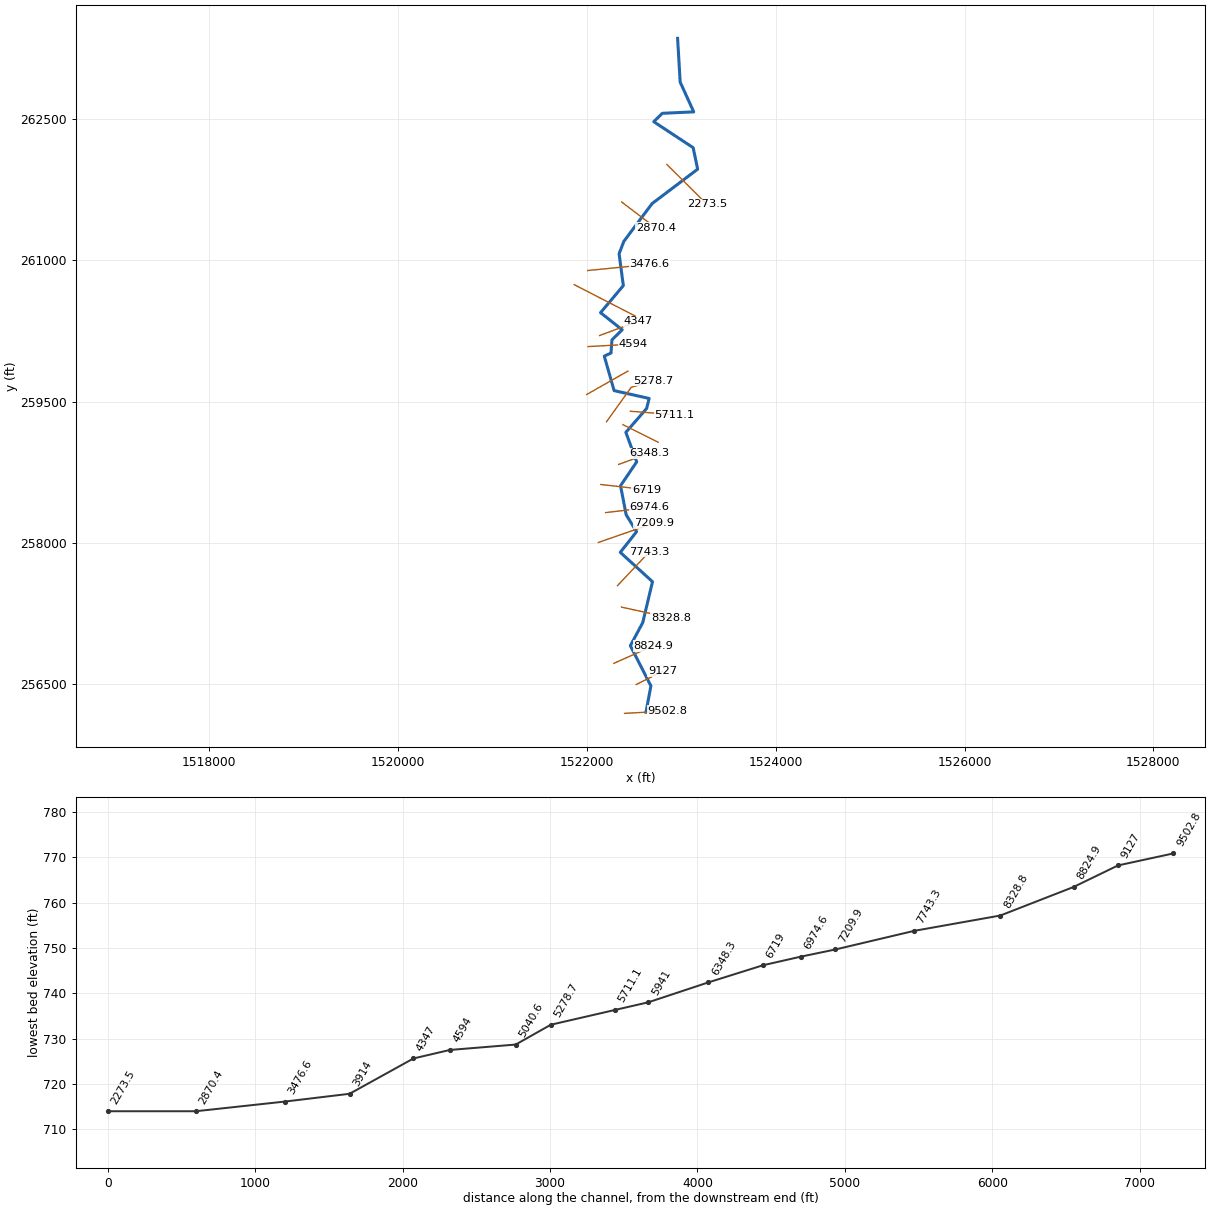
--- THRDRN.prj (project) ---

Proj Title=THRDRN
Current Plan=p01
Default Exp/Contr=0,0
English Units
Geom File=g01
Flow File=f01
Plan File=p01
BEGIN DESCRIPTION:
END DESCRIPTION:
DSS Export Rating Curves= 0
DSS Export Rating Curve Sorted= 0
DSS Export Volume Flow Curves= 0
DXF OffsetX= 0
DXF OffsetY= 0
DXF ScaleX= 0
DXF ScaleY= 0

--- THRDRN.p01 (plan) ---

Plan Title=Floodplain
Program Version=4.00
Geom File=g01
Flow File=f01
K Sum by GR=0
Std Step Tol=0.01
Critical Tol=0.01
Num of Std Step Trials=20
Max Error Tol=0.3
Flow Tol Ratio=0.001
Split Flow NTrial=30
Split Flow Tol=0.02
Split Flow Ratio=0.02
Log Output Level=0
Friction Slope Method=1
Unsteady Friction Slope Method=2
Unsteady Bridges Friction Slope Method=1
Global Log Level=0
CheckData=False
Run HTab=0
Run UNet=0
Run PostProcess=0
UNET Theta=0
UNET Theta Warmup=0
UNET ZTol=0
UNET ZSATol=0
UNET MxIter=0
UNET MaxInSteps=0
UNET DtIC=0
UNET DtMin=0
UNET MaxCRTS=0
UNET WFStab=0
UNET SFStab=0
UNET WFX=0
UNET SFX=0
UNET DSS MLevel=0
UNET DZMax Abort=0
UNET Convert EG Bridges=0
UNET Use Existing IB Tables=0
UNET Froude Limit=0
UNET Froude Power=0
Write IC File=0
Echo Input=False
Echo Output=False
Write Detailed=0

--- THRDRN.f01 (steady flow) ---

Flow Title=NFF Regression Equation
Program Version=4.00
Number of Profiles=1
Profile Names=P100yr
River Rch & RM=THRDRN,Main      ,9502.8
894.3434
River Rch & RM=THRDRN,Main      ,6719
960.2669
River Rch & RM=THRDRN,Main      ,3914
1065.849
River Rch & RM=THRDRN,Main      ,3476.6
1190.119
River Rch & RM=THRDRN,Main      ,2273.5
1205.274
Boundary for River Rch & Prof#=THRDRN,Main      ,1
Up Type=0
Dn Type=3
Dn Slope=0.002281

--- THRDRN.g01 (geometry) ---

Geom Title=USGS 10m DEM
Program Version=4.10

River Reach=THRDRN          ,Main
Reach XY= 30
     1522624.895      256202.565     1522677.128      256481.729
     1522459.692      256908.307     1522590.568      257153.726
      1522694.04      257588.101      1522352.72      257899.559
     1522524.943      258118.309      1522415.22      258298.518
     1522355.498      258606.851     1522526.486      258860.189
     1522411.783      259173.674     1522631.726      259426.759
     1522658.311      259533.396     1522287.165      259616.616
     1522183.094      259983.071     1522254.274      260015.189
     1522264.691       260155.38     1522372.764       260262.15
     1522143.706      260443.972     1522385.025      260731.298
     1522340.146      261070.274     1522390.928      261201.784
     1522689.105      261601.524     1523172.178      261967.409
     1523124.741      262195.512     1522707.206      262471.553
     1522798.352      262560.529     1523130.383       262575.72
     1522987.154       262892.56     1522959.884      263356.401

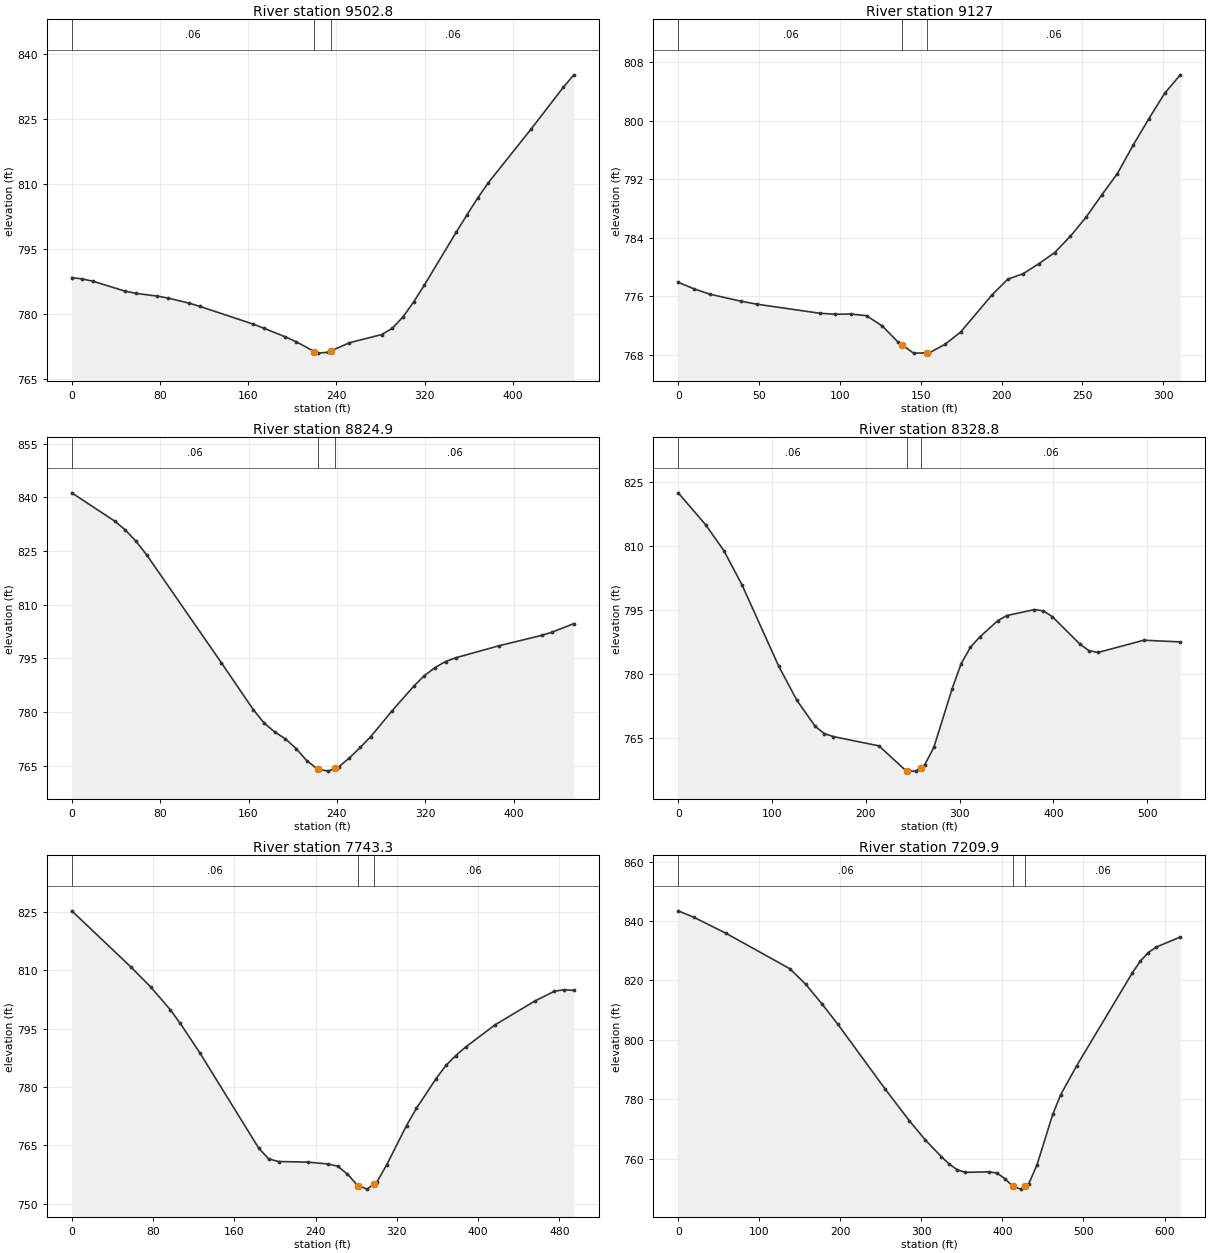
Type RM Length L Ch R = 1 ,9502.8  ,366.4,375.8,385
XS GIS Cut Line= 2
     1522397.691      256190.154     1522852.401      256215.523
#Sta/Elev= 30
       0  788.33     9.7     788    19.4  787.47    48.4  785.19    58.1  784.68
    77.5  784.05    87.2  783.61   106.6  782.41   116.3  781.66   164.7  777.57
   174.4  776.62   193.8  774.63   203.5  773.52     220  771.25   222.9  770.88
   232.6  771.08     235  771.37   251.9  773.28     281  775.16   290.7  776.61
   300.4  779.24   310.1   782.7   319.8   786.6   348.8  798.85   358.5  802.83
   368.2   806.7   377.9  810.26   416.7  822.65   445.7  832.23   455.4  835.15
#Mann= 3 , 0 , 0
       0     .06       0     220    .045       0     235     .06       0
Bank Sta=220,235
XS Rating Curve= 0 ,0
Exp/Cntr=0.3,0.1

Type RM Length L Ch R = 1 ,9127    ,303,302.1,300.9
XS GIS Cut Line= 2
     1522521.714      256496.779     1522799.492      256635.668
#Sta/Elev= 30
       0  777.92     9.7  777.03    19.4   776.3    38.8  775.33    48.5  774.93
    87.4  773.69      97  773.55   106.8  773.58   116.5  773.35   126.2  771.95
   135.9  769.76   138.7  769.32   145.6  768.23   153.7  768.26   155.3  768.27
     165  769.43   174.7  771.11   194.1   776.2   203.8  778.33   213.5  779.11
   223.2  780.48   232.9  781.99   242.6  784.22   252.3  786.83     262  789.87
   271.7   792.8   281.4  796.67   291.2  800.32   300.9  803.77   310.6   806.3
#Mann= 3 , 0 , 0
       0     .06       0   138.7    .045       0   153.7     .06       0
Bank Sta=138.7,153.7
XS Rating Curve= 0 ,0
Exp/Cntr=0.3,0.1

Type RM Length L Ch R = 1 ,8824.9  ,509.4,496.1,481.8
XS GIS Cut Line= 2
     1522284.446      256721.316      1522699.63       256906.13
#Sta/Elev= 30
       0  841.28    38.7  833.41    48.4  830.92      58   827.8    67.7  823.99
   135.4  793.79   164.4  780.63     174  776.96   183.7  774.41   193.4   772.5
   203.1  769.78   212.7   766.4   222.4  764.05   223.3     764   232.1  763.47
   238.3  764.24   241.7  764.66   251.4  767.19   261.1  770.09   270.7  773.14
   290.1  780.39   309.4  787.16   319.1  790.14   328.8  792.42   338.4  794.11
   348.1  795.21   386.8  798.53   425.4  801.43   435.1  802.36   454.5  804.71
#Mann= 3 , 0 , 0
       0     .06       0   223.3    .045       0   238.3     .06       0
Bank Sta=223.3,238.3
XS Rating Curve= 0 ,0
Exp/Cntr=0.3,0.1

Type RM Length L Ch R = 1 ,8328.8  ,561.3,585.4,608.4
XS GIS Cut Line= 2
     1522365.055      257318.666     1522887.744      257203.087
#Sta/Elev= 30
       0  822.48    29.2     815    48.7   808.9    68.1  800.83   107.1  781.82
   126.5   773.8     146   767.7   155.7  765.99   165.5  765.28   214.1   763.1
   243.3  757.18   243.4  757.18   253.1  757.18   258.4  757.99   262.8  758.66
   272.5  762.75     292  776.49   301.7  782.43   311.5  786.23   321.2   788.6
   340.7  792.48   350.4  793.69   379.6  795.08   389.3  794.78     399   793.4
   428.2     787     438  785.43   447.7  785.03   496.4   787.9   535.3   787.5
#Mann= 3 , 0 , 0
       0     .06       0   243.4    .045       0   258.4     .06       0
Bank Sta=243.4,258.4
XS Rating Curve= 0 ,0
Exp/Cntr=0.3,0.1

Type RM Length L Ch R = 1 ,7743.3  ,544.1,533.4,518.2
XS GIS Cut Line= 2
     1522323.219      257546.385      1522662.05      257906.212
#Sta/Elev= 30
       0  825.29    58.2  810.87    77.5  805.78    96.9  799.91   106.6  796.44
     126  788.83   184.1  764.29   193.8  761.56   203.5  760.88   232.6  760.73
     252  760.25   261.7  759.69   271.4  757.64     281  754.84   282.2  754.71
   290.7  753.79   297.2  755.02   300.4  755.63   310.1   760.1   329.5  770.12
   339.2  774.54   358.6  782.18   368.3  785.57     378  788.12   387.6  790.28
   416.7  796.01   455.5  802.07   474.9  804.61   484.6  805.03   494.2  804.83
#Mann= 3 , 0 , 0
       0     .06       0   282.2    .045       0   297.2     .06       0
Bank Sta=282.2,297.2
XS Rating Curve= 0 ,0
Exp/Cntr=0.3,0.1

Type RM Length L Ch R = 1 ,7209.9  ,240.2,235.4,230
XS GIS Cut Line= 2
     1522120.161       258004.68     1522705.381      258207.786
#Sta/Elev= 30
       0  843.44    19.7  841.22      59  835.87   137.7  823.94   157.3   818.7
     177  812.21   196.7  805.32   255.6  783.31   285.2  772.72   304.8  766.27
   324.5  760.67   334.3  758.16   344.2  756.22     354  755.34   383.5  755.52
   393.3  755.11   403.1  753.24   412.9   750.6   422.8  749.69   427.9  750.67
   432.6  751.58   442.5  757.73   462.1  774.89     472  781.56   491.6  791.25
   560.5  822.64   570.3  826.55   580.1   829.4     590  831.26   619.5  834.62
#Mann= 3 , 0 , 0
       0     .06       0   412.9    .045       0   427.9     .06       0
Bank Sta=412.9,427.9
XS Rating Curve= 0 ,0
Exp/Cntr=0.3,0.1

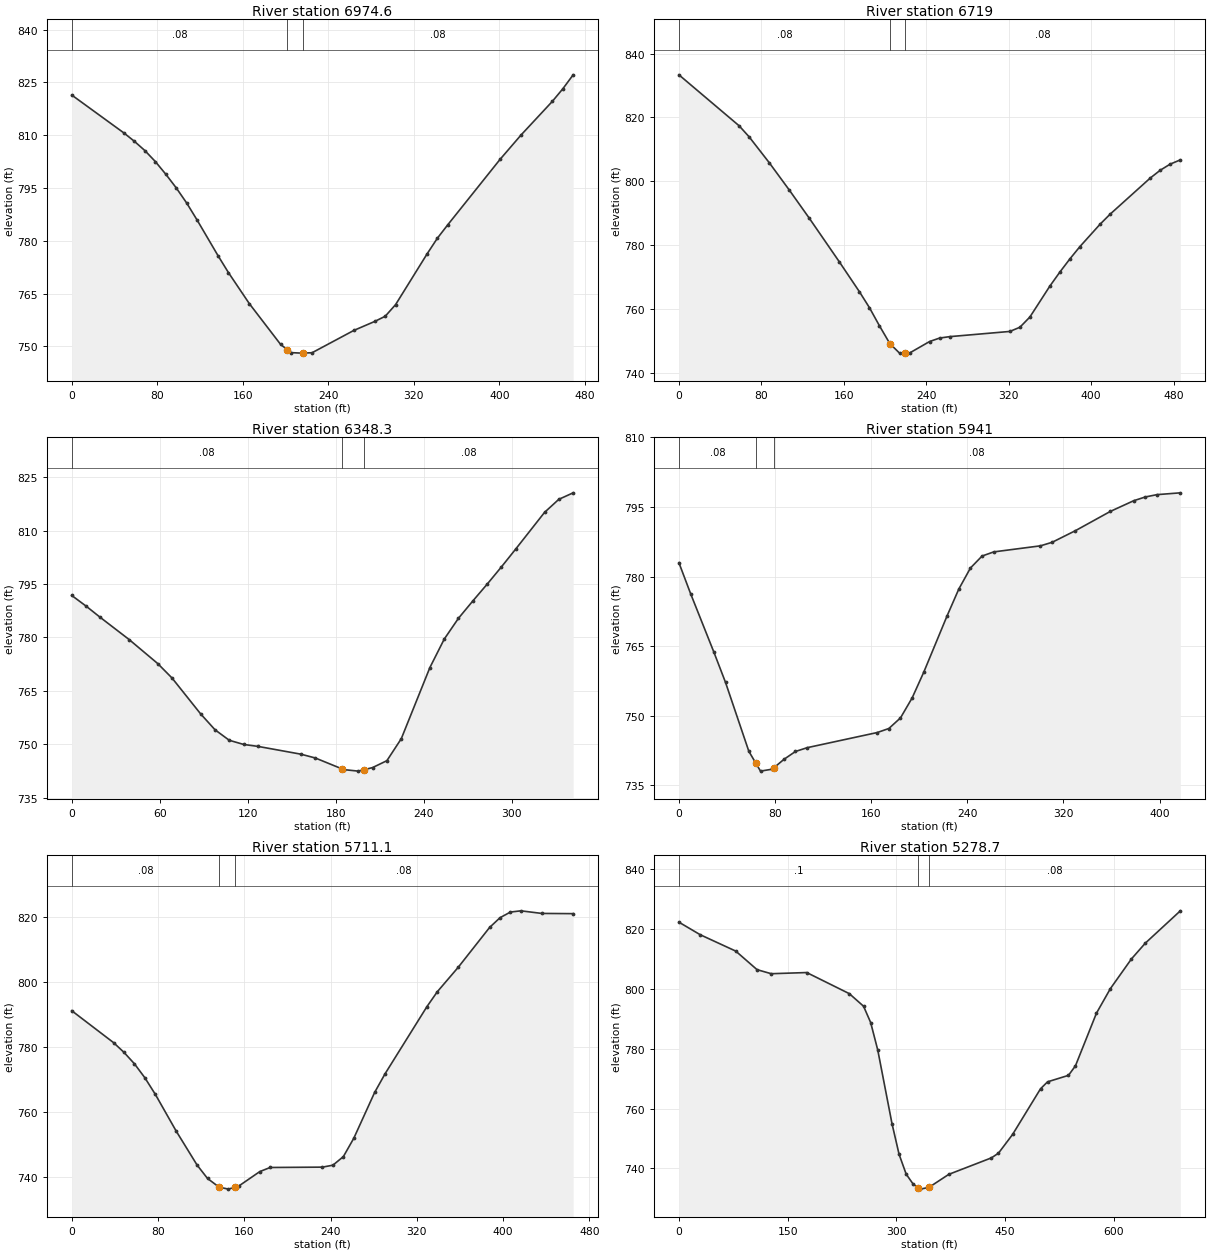
Type RM Length L Ch R = 1 ,6974.6  ,260.8,255.6,250.3
XS GIS Cut Line= 2
     1522197.586      258321.699      1522663.48      258375.978
#Sta/Elev= 30
       0   821.4    48.9  810.61    58.6  808.26    68.4  805.63    78.2  802.51
      88   798.9    97.7  795.05   107.5  790.74   117.3  785.88   136.8  775.79
   146.6  770.96   166.1  762.16   195.4  750.56   201.5  749.12   205.2  748.24
     215   748.1   216.5  748.12   224.8  748.21   263.8  754.54   283.4   757.1
   293.2  758.57   302.9  761.87   332.2   776.2     342  780.74   351.8  784.58
   400.6  803.12   420.2  810.03   449.5  819.59   459.3  823.16     469  827.14
#Mann= 3 , 0 , 0
       0     .08       0   201.5    .045       0   216.5     .08       0
Bank Sta=201.5,216.5
XS Rating Curve= 0 ,0
Exp/Cntr=0.3,0.1

Type RM Length L Ch R = 1 ,6719    ,360,370.7,381.3
XS GIS Cut Line= 2
     1522145.761      258620.138     1522629.182      258565.028
#Sta/Elev= 30
       0  833.35    58.4   817.4    68.1  813.95    87.6  805.86     107  797.32
   126.5  788.46   155.7  774.78   175.2  765.42   184.9  760.44   194.6  754.77
   204.7  749.19   214.1  746.21   219.7  746.23   223.8  746.24   243.3  749.85
     253  750.93   262.7  751.37   321.1     753   330.9  754.31   340.6  757.52
     360  767.21   369.8  771.64   379.5  775.75   389.2  779.59   408.7  786.57
   418.4   789.7   457.4  801.03   467.1  803.48   476.8   805.4   486.6  806.72
#Mann= 3 , 0 , 0
       0     .08       0   204.7    .045       0   219.7     .08       0
Bank Sta=204.7,219.7
XS Rating Curve= 0 ,0
Exp/Cntr=0.3,0.1

Type RM Length L Ch R = 1 ,6348.3  ,416.8,407.3,376.8
XS GIS Cut Line= 2
     1522335.915      258833.213     1522657.095      258950.401
#Sta/Elev= 30
       0   791.8     9.8   788.8    19.5  785.62    39.1  779.42    58.6  772.67
    68.4  768.59    87.9  758.51    97.7  754.05   107.4   751.1   117.2  749.93
     127  749.38   156.3  747.19   166.1  746.12   184.3  743.06   185.6  742.85
   195.4  742.43   199.3  742.83   205.1  743.42   214.9  745.37   224.7  751.54
   244.2  771.53     254  779.54   263.7  785.39   273.5  790.26   283.3  794.99
     293  799.83   302.8  804.88   322.4  815.15   332.1  818.81   341.9  820.64
#Mann= 3 , 0 , 0
       0     .08       0   184.3    .045       0   199.3     .08       0
Bank Sta=184.3,199.3
XS Rating Curve= 0 ,0
Exp/Cntr=0.3,0.1

Type RM Length L Ch R = 1 ,5941    ,219.9,229.9,239.2
XS GIS Cut Line= 2
     1522381.054      259255.088     1522754.317      259068.456
#Sta/Elev= 30
       0  782.99     9.7  776.33    29.1   763.7    38.8  757.16    58.2  742.31
    64.1  739.71    67.9  738.04    77.6  738.46    79.1  738.78    87.4  740.58
      97  742.28   106.8   743.1     165  746.36   174.7  747.23   184.4  749.52
   194.1  753.83   203.8   759.4   223.2  771.54   232.9  777.29   242.6  781.84
   252.3  784.43     262  785.32   300.9  786.63   310.6  787.39     330   789.9
   359.1  794.06   378.5  796.36   388.2  797.17   397.9  797.67   417.3  798.06
#Mann= 3 , 0 , 0
       0     .08       0    64.1    .045       0    79.1     .08       0
Bank Sta=64.1,79.1
XS Rating Curve= 0 ,0
Exp/Cntr=0.3,0.1

Type RM Length L Ch R = 1 ,5711.1  ,409.7,432.4,454.6
XS GIS Cut Line= 2
     1522460.231      259397.527     1522923.773      259361.069
#Sta/Elev= 30
       0  791.23    38.8   781.4    48.4  778.43    58.1  774.91    67.8   770.6
    77.5   765.5    96.9  754.16   116.2  743.75   125.9  739.61   136.6  736.94
   145.3  736.32   151.6  736.95     155  737.29   174.4  741.72     184  742.98
   232.5  743.09   242.2  743.69   251.9  746.33   261.6     752   280.9  766.08
   290.6  771.84   329.4  792.49     339  797.06   358.4  804.59   387.5  816.85
   397.2  819.86   406.8  821.59   416.5  821.97   435.9  821.17     465   821.1
#Mann= 3 , 0 , 0
       0     .08       0   136.6    .045       0   151.6     .08       0
Bank Sta=136.6,151.6
XS Rating Curve= 0 ,0
Exp/Cntr=0.3,0.1

Type RM Length L Ch R = 1 ,5278.7  ,248,238,228.1
XS GIS Cut Line= 3
     1522206.483        259285.4     1522468.756      259651.842
     1522699.814      259720.444
#Sta/Elev= 30
       0  822.31    29.4  818.11    78.4  812.64   107.8  806.43   127.4  805.08
   176.3  805.47   235.1  798.41   254.7  794.21   264.5  788.77   274.3  779.56
   293.9  755.01   303.7  744.72   313.5  738.09   323.3   734.7     330  733.59
   333.1  733.08     345  733.68   372.3  738.02     431  743.52   440.8  745.09
   460.3  751.36   498.8  766.61   508.5  768.94   537.4  771.11     547  774.29
     576   791.9   595.2   800.1   624.2  810.01   643.4   815.3   691.7   826.1
#Mann= 3 , 0 , 0
       0      .1       0     330    .045       0     345     .08       0
Bank Sta=330,345
XS Rating Curve= 0 ,0
Exp/Cntr=0.3,0.1

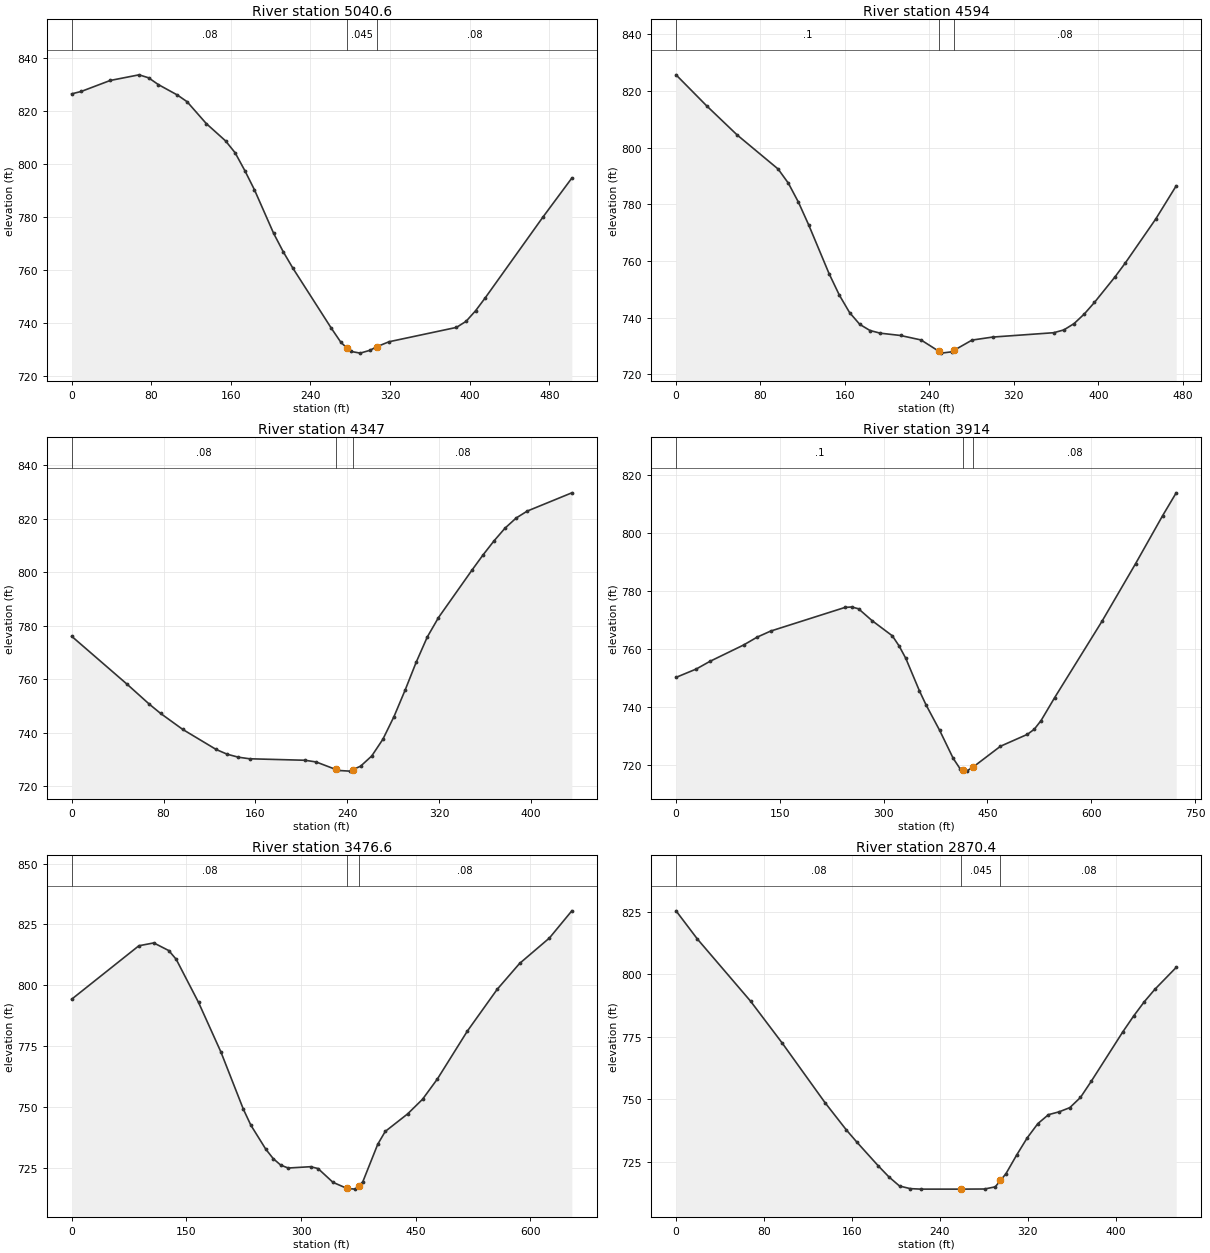
Type RM Length L Ch R = 1 ,5040.6  ,456.3,446.7,434.7
XS GIS Cut Line= 2
     1521996.287      259574.949     1522433.137      259823.665
#Sta/Elev= 30
       0   826.4     9.7  827.32    38.7  831.44    67.7  833.57    77.3  832.45
      87  829.92   106.3  825.95     116  823.44   135.3   815.2   154.7  808.67
   164.3  804.19     174  797.51   183.7  790.26     203  773.83   212.7  766.86
   222.3  760.74     261  738.08   270.7  732.72   277.2  730.48   280.4  729.37
     290  728.71   299.7  729.77     307731.1773     319     733   386.7   738.4
   396.4  740.69     406   744.7   415.7  749.56   473.7     780   502.7  794.67
#Mann= 3 , 0 , 0
       0     .08       0   277.2    .045       0     307     .08       0
Bank Sta=277.2,307
XS Rating Curve= 0 ,0
Exp/Cntr=0.3,0.1

Type RM Length L Ch R = 1 ,4594    ,238.2,247,251.4
XS GIS Cut Line= 2
      1522012.13      260084.081      1522485.22      260110.123
#Sta/Elev= 30
       0  825.67      29  814.74      58  804.43    96.7  792.45   106.4  787.46
     116  780.71   125.7  772.71     145  755.53   154.7  747.98   164.4  741.82
     174  737.68   183.7   735.5   193.4  734.56   212.7  733.74   232.1  732.16
   248.7  728.24   251.4  727.52   261.1  727.98   263.7  728.59   280.4  732.12
   299.8  733.18   357.8  734.72   367.4  735.71   377.1  737.95   386.8  741.35
   396.4  745.42   415.8   754.4   425.5  759.27   454.5  774.87   473.8  786.52
#Mann= 3 , 0 , 0
       0      .1       0   248.7    .045       0   263.7     .08       0
Bank Sta=248.7,263.7
XS Rating Curve= 0 ,0
Exp/Cntr=0.3,0.1

Type RM Length L Ch R = 1 ,4347    ,450.8,433.1,413.8
XS GIS Cut Line= 2
     1522133.658      260201.269     1522541.644      260353.179
#Sta/Elev= 30
       0  776.06    48.4  758.07    67.7  750.63    77.4  747.22    96.7  741.23
   125.8  733.73   135.4  731.96   145.1  730.85   154.8  730.26   203.2   729.7
   212.8  729.07     230  726.25   232.2  725.89   241.9  725.64     245  726.24
   251.5  727.49   261.2   731.3   270.9  737.55   280.6  746.05   290.2  755.86
   299.9  766.35   309.6  775.82   319.3  783.04   348.3  800.69     358  806.42
   367.6   811.7   377.3  816.51     387  820.29   396.6  822.87   435.4  829.69
#Mann= 3 , 0 , 0
       0     .08       0     230    .045       0     245     .08       0
Bank Sta=230,245
XS Rating Curve= 0 ,0
Exp/Cntr=0.3,0.1

Type RM Length L Ch R = 1 ,3914    ,424,437.3,449.8
XS GIS Cut Line= 2
     1521864.292      260741.607     1522506.798      260410.759
#Sta/Elev= 30
       0  750.24    29.3  753.14    48.8  755.76    97.7  761.44   117.2  764.15
   136.7  766.24   244.2  774.42   253.9  774.57   263.7  773.94   283.2  769.86
   312.5  764.61   322.3  761.11     332  756.81   351.6  745.64   361.3  740.71
   380.9  731.94   400.4   722.3   410.2  718.75   414.5  718.35   419.9  717.85
   429.5  719.31   468.8  726.45   507.8  730.57   517.6  732.32   527.4  735.31
   546.9  743.18   615.3  769.56   664.1  789.58   703.2  806.17   722.7  814.01
#Mann= 3 , 0 , 0
       0      .1       0   414.5    .045       0   429.5     .08       0
Bank Sta=414.5,429.5
XS Rating Curve= 0 ,0
Exp/Cntr=0.3,0.1

Type RM Length L Ch R = 1 ,3476.6  ,623,606.3,589.1
XS GIS Cut Line= 2
      1522007.79      260891.373     1522658.831      260956.477
#Sta/Elev= 30
       0  794.25    87.9  816.23   107.4   817.4     127  814.26   136.7  810.69
     166   792.9   195.3  772.49   224.6     749   234.4  742.44   253.9  732.58
   263.7  728.68   273.4  726.04   283.2  724.82   312.5  725.36   322.3   724.6
   341.8  718.94   360.4   716.4   371.1  716.14   375.4  717.47   380.8  719.13
   400.4   734.6   410.2  739.87   439.4  747.06     459   753.1   478.5  761.48
   517.6  781.13   556.6   798.3   585.9  808.94     625  819.43   654.3   830.6
#Mann= 3 , 0 , 0
       0     .08       0   360.4    .045       0   375.4     .08       0
Bank Sta=360.4,375.4
XS Rating Curve= 0 ,0
Exp/Cntr=0.3,0.1

Type RM Length L Ch R = 1 ,2870.4  ,599.7,596.9,594
XS GIS Cut Line= 2
     1522367.462      261618.637     1522729.636       261343.22
#Sta/Elev= 30
       0  825.42    19.4  814.14    67.8  789.25    96.8  772.35   135.5  748.64
   154.9  737.72   164.6  732.77   183.9  723.35   193.6  718.92   203.3  715.25
     213   714.2   222.7     714   259.1     714   280.7  714.05   290.4  714.92
   295.1717.4638   300.1  720.17   309.8   727.6   319.5  734.55   329.2  740.26
   338.8  743.81   348.5  744.95   358.2  746.62   367.9   750.7   377.6  757.09
   406.6  777.08   416.3  783.32     426  789.04   435.6     794     455  802.77
#Mann= 3 , 0 , 0
       0     .08       0   259.1    .045       0   295.1     .08       0
Bank Sta=259.1,295.1
XS Rating Curve= 0 ,0
Exp/Cntr=0.3,0.1

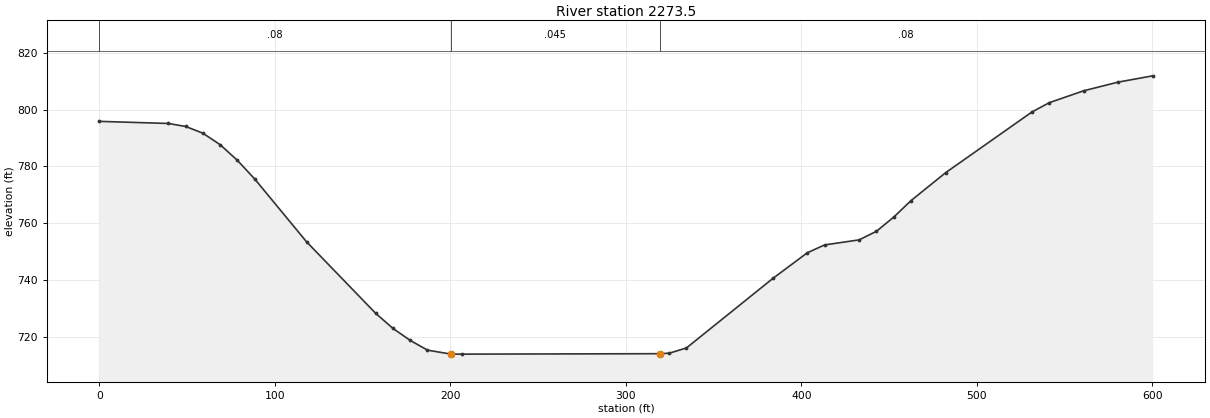
Type RM Length L Ch R = 1 ,2273.5  ,2250.6,2273.5,2295.9
XS GIS Cut Line= 2
     1522846.155      262017.409     1523271.714      261594.001
#Sta/Elev= 30
       0  795.86    39.4  795.11    49.2  794.06      59   791.7    68.9  787.63
    78.7  782.13    88.6  775.55   118.1  753.49   157.5  728.34   167.3  723.06
   177.1  718.85     187   715.4   200.4714.0063   206.7     714   319.4  714.15
   324.8  714.33   334.6  716.18   383.8  740.61   403.5  749.66   413.3   752.4
     433  754.18   442.8  757.18   452.7  762.19   462.5  767.96   482.2  777.77
   531.4  799.13   541.3  802.42     561  806.62   580.6  809.66   600.3  811.87
#Mann= 3 , 0 , 0
       0     .08       0   200.4    .045       0   319.4     .08       0
Bank Sta=200.4,319.4
XS Rating Curve= 0 ,0
Exp/Cntr=0.3,0.1

Chan Stop Cuts=-1
Use User Specified Reach Order=0
Composite Channel Slope=5